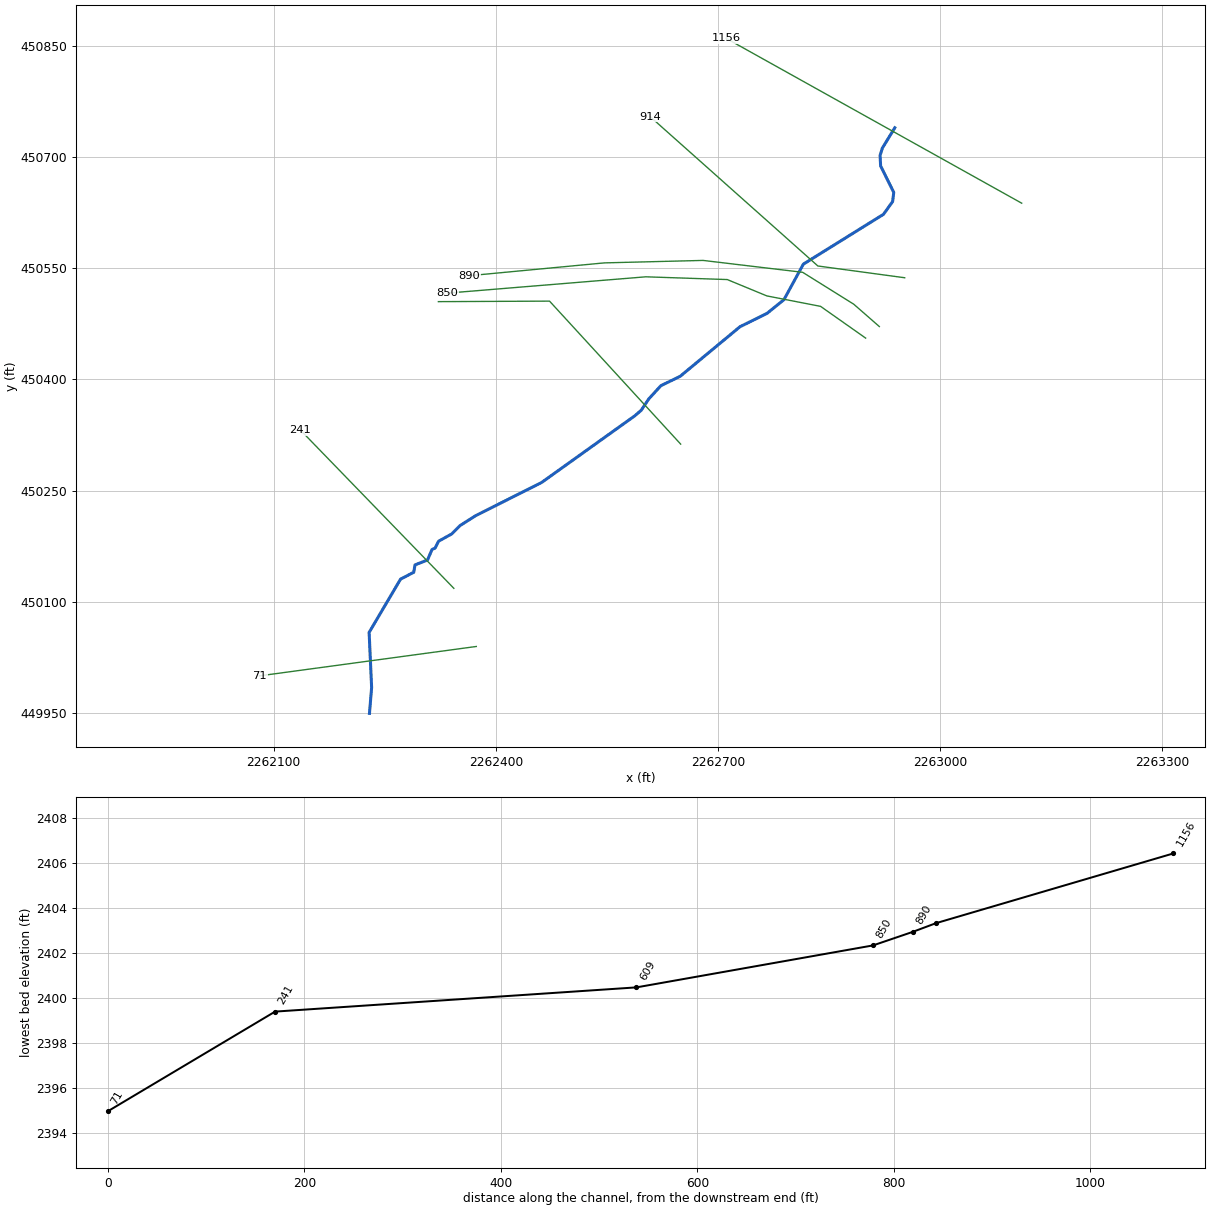
--- BRWNSCK1.prj (project) ---

Proj Title=BRWNSCK1
Current Plan=p01
Default Exp/Contr=0,0
English Units
Geom File=g01
Flow File=f01
Plan File=p01
BEGIN DESCRIPTION:
----------MODEL BY WOOD PLC 2021----------
Stream Name: Browns Creek Upper Reach
Flood Zone: Enhanced Approximate
Pocahontas County, WV
HEC-RAS Version: RAS 6.1
Vertical Datum: NAVD88
Projection: NAD 1983 StatePlane West Virginia S FIPS 4702 (US Feet)
Terrain: 1-meter LIDAR (FEMA Region III 3DEP collected 2016-2018)
Land Use: 2019 NLCD
Hydrologic Method:
WV SIR2010-5033 regression equations
Model Notes:
Normal depth tie in with Browns Creek Lower Reach and Browns Creek Tributary 1.  Browns Creek Tributary 1 has a larger drainage area at the confluence with Browns Creek
END DESCRIPTION:
DSS Export Rating Curves= 0
DSS Export Rating Curve Sorted= 0
DSS Export Volume Flow Curves= 0
DXF OffsetX= 0
DXF OffsetY= 0
DXF ScaleX= 0
DXF ScaleY= 0

--- BRWNSCK1.p01 (plan) ---

Plan Title=Floodplain
Program Version=6.10
Short Identifier=Floodplain
Geom File=g01
Flow File=f01
Subcritical Flow
K Sum by GR= 0
Std Step Tol= 0.01
Critical Tol= 0.01
Num of Std Step Trials= 20
Max Error Tol= 0.3
Flow Tol Ratio= 0.001
Split Flow NTrial= 30
Split Flow Tol= 0.02
Split Flow Ratio= 0.02
Log Output Level= 0
Friction Slope Method= 1
Unsteady Friction Slope Method= 2
Unsteady Bridges Friction Slope Method= 1
Parabolic Critical Depth
Global Vel Dist= 0 , 0 , 0
Global Log Level= 0
CheckData=True
Encroach Param=-1 ,0,0, 0
Mapping Interval=1HOUR
Computation Time Step Use Courant=        0
Computation Time Step Use Time Series=    0
Computation Time Step Count To Double=0
Computation Time Step Max Doubling=0
Computation Time Step Max Halving=0
Computation Time Step Residence Courant=0
Run HTab= 0
Run UNet= 0
Run Sediment= 0
Run PostProcess= 0
Run WQNet= 0
Run RASMapper=-1
UNET Theta= 0
UNET Theta Warmup= 0
UNET ZTol= 0
UNET ZSATol= 0
UNET MxIter= 0
UNET Max Iter WO Improvement= 0
UNET MaxInSteps= 0
UNET DtIC= 0
UNET DtMin= 0
UNET MaxCRTS= 0
UNET WFStab= 0
UNET SFStab= 0
UNET WFX= 1
UNET SFX= 1
UNET Gravity=32.174
UNET 1D Methodology=Finite Difference
UNET DSS MLevel= 1
UNET Pardiso=0
UNET DZMax Abort= 0
UNET Use Existing IB Tables= 0
UNET Froude Reduction=False
UNET Froude Limit= 0
UNET Froude Power= 0
UNET D1 Cores= 0
UNET WindReference=Eulerian
UNET WindDragFormulation=Hsu (1988)
UNET D2 Coriolis=0
UNET D2 Cores= 0
UNET D2 Theta= 1
UNET D2 Theta Warmup= 1
UNET D2 Z Tol= 0.01
UNET D2 Volume Tol= 0.01
UNET D2 Max Iterations= 20
UNET D2 Equation= 0
UNET D2 RampUpFraction=0.1
UNET D2 TimeSlices= 1
UNET D2 Turbulence Formulation=Non-Conservative (original)
UNET D2 Eddy Viscosity=0.3
UNET D2 Transverse Eddy Viscosity=0.1
UNET D2 Smagorinsky Mixing=0
UNET D2 BCVolumeCheck=0
UNET D2 Cores=0
UNET D2 SolverType=PARDISO (Direct)
UNET D2 Minimum Iterations= 2147483647
UNET D2 Maximum Iterations= 2147483647
UNET D2 Restart Number= 10
UNET D2 Relaxation Coeff=1.3
UNET D2 SOR Precondition Iterations= 10
UNET D2 ILUT Maximum Fill= 8
UNET D2 ILUT Tolerance=1E-08
UNET D1D2 MaxIter= 0
UNET D1D2 ZTol=0.01
UNET D1D2 QTol=0.1
UNET D1D2 MinQTol=1
Write IC File= 0
Write IC File at Fixed DateTime=0
Write IC File at Sim End=0
Echo Input=False
Echo Parameters=False
Echo Output=False
Write Detailed= 0
HDF Write Warmup=0
HDF Write Time Slices=0
HDF Flush=0
HDF Compression= 1
HDF Chunk Size= 1
HDF Spatial Parts= 1
HDF Use Max Rows=0
HDF Fixed Rows= 1
Calibration Method= 0
Calibration Iterations= 20
Calibration Max Change=0.05
Calibration Tolerance=0.2
Calibration Maximum=1.5
Calibration Minimum=0.5
Calibration Optimization Method= 1
WQ AD Non Conservative
WQ ULTIMATE=-1
WQ Max Comp Step=1HOUR
WQ Output Interval=15MIN
WQ Output Selected Increments= 0
WQ Output face flow=0
WQ Output face velocity=0
WQ Output face area=0
WQ Output face dispersion=0
WQ Output cell volume=0
WQ Output cell surface area=0
WQ Output cell continuity=0
WQ Output cumulative cell continuity=0
WQ Output face conc=0
WQ Output face dconc_dx=0
WQ Output face courant=0
WQ Output face peclet=0
WQ Output face adv mass=0
WQ Output face disp mass=0
WQ Output cell mass=0
WQ Output cell source sink temp=0
WQ Output nsm pathways=0
WQ Output nsm derived pathways=0
WQ Create Restart=0
WQ Fixed Restart=0
WQ System Summary=0
WQ Write To DSS=0
Sorting and Armoring Iterations= 10
XS Update Threshold= 0.02
Bed Roughness Predictor= 0
Hydraulics Update Threshold= 0.02
Energy Slope Method= 1
Volume Change Method= 1
Sediment Retention Method= 0
Sediment TS Multiplier= 1
Warm Up Method= 0
XS Weighting Method= 0
Number of US Weighted Cross Sections= 1
Number of DS Weighted Cross Sections= 1
Upstream XS Weight=0
Main XS Weight=1
Downstream XS Weight=0
Number of DS XS's Weighted with US Boundary= 1
Upstream Boundary Weight= 1
Weight of XSs Associated with US Boundary= 0
Number of US XS's Weighted with DS Boundary= 1
Downstream Boundary Weight= 0.5
Weight of XSs Associated with DS Boundary= 0.5
Percentile Method= 0
Sediment Output Level= 3
Mass or Volume Output= 0
Output Increment Type= 1
Profile and TS Output Increment= 1
Transport Output Increment 1
XS Output Flag= 0
XS Output Increment= 10
Read HDF5 Sediment Hotstart= 0
Sediment Hotstart Type= 0
Write Gradation File= 0
Read Gradation Hotstart= 0
Write HDF5 File= 1
Write Binary Output= 1
Write DSS Sediment File= 0
DSS Sediment Output Type= 1
SV Curve= 0
Specific Gage Flag= 0
Subcell Erosion Methods= 0
Subcell Deposition Methods= 0
Advection Scheme= 1
Matrix Solver= 0
Implicit Weighting Factor= 1
Maximum Outer Loop Convergence Iterations= 5
Convergence Maximum Absolute= 0.001
Convergence RMSE= 0.0001
Grain Fractions Max Abs Error= 0.001
Max Subgrid Regions= 1
Max Subgrid Length Scale= 3.402823E+38
Initial Layer Thickness= 3.402823E+38
Min Layer Thickness= 3.402823E+38
Max Layer Thickness= 3.402823E+38
Number of Layers= 5

--- BRWNSCK1.f01 (steady flow) ---

Flow Title=Flow
Program Version=6.10
Number of Profiles= 6
Profile Names=01pct,10pct,04pct,02pct,0_2pct,01plus
River Rch & RM=BRWNSCKT1,Main            ,1156
     283     145     196     238     400     418
River Rch & RM=BRWNSCK1,Main            ,1156
     283     145     196     238     400     418
Boundary for River Rch & Prof#=BRWNSCK1,Main            , 1
Up Type= 0
Dn Type= 3
Dn Slope=0.0268
Boundary for River Rch & Prof#=BRWNSCK1,Main            , 2
Up Type= 0
Dn Type= 3
Dn Slope=0.0268
Boundary for River Rch & Prof#=BRWNSCK1,Main            , 3
Up Type= 0
Dn Type= 3
Dn Slope=0.0268
Boundary for River Rch & Prof#=BRWNSCK1,Main            , 4
Up Type= 0
Dn Type= 3
Dn Slope=0.0268
Boundary for River Rch & Prof#=BRWNSCK1,Main            , 5
Up Type= 0
Dn Type= 3
Dn Slope=0.0268
Boundary for River Rch & Prof#=BRWNSCK1,Main            , 6
Up Type= 0
Dn Type= 3
Dn Slope=0.0268
DSS Import GetInterval= 0
DSS Import GetPeak= 0
DSS Import FillOption= 0

--- BRWNSCK1.g01 (geometry) ---

Geom Title=Geometry
Program Version=6.10

River Reach=BRWNSCK1        ,Main
Reach XY= 30
2262938.90322074450739.9471135382262922.12479321450712.554980058
2262919.01730193 450702.64985161      2262919.74      450688.374
     2262937.477      450652.659      2262935.98       450640.33
     2262923.573      450623.036     2262815.391       450555.78
2262789.17601115450507.761367105     2262766.447      450489.367
     2262729.865      450471.267     2262648.994      450404.254
     2262623.029      450391.645     2262606.591      450373.725
     2262596.438      450358.395     2262587.537      450350.781
     2262462.017      450260.958      2262372.85      450216.079
     2262351.852      450202.7652262340.50787041450191.417344667
2262322.74662857 450181.566571882262318.11975044450172.312815626
2262313.91856091450170.4419282482262307.82121526450156.193369247
2262290.95549821450149.6261873892262289.16444862450139.626160469
2262271.38456296450130.334383577     2262228.966      450058.403
      2262232.33       449984.112262229.43662852449949.078014498

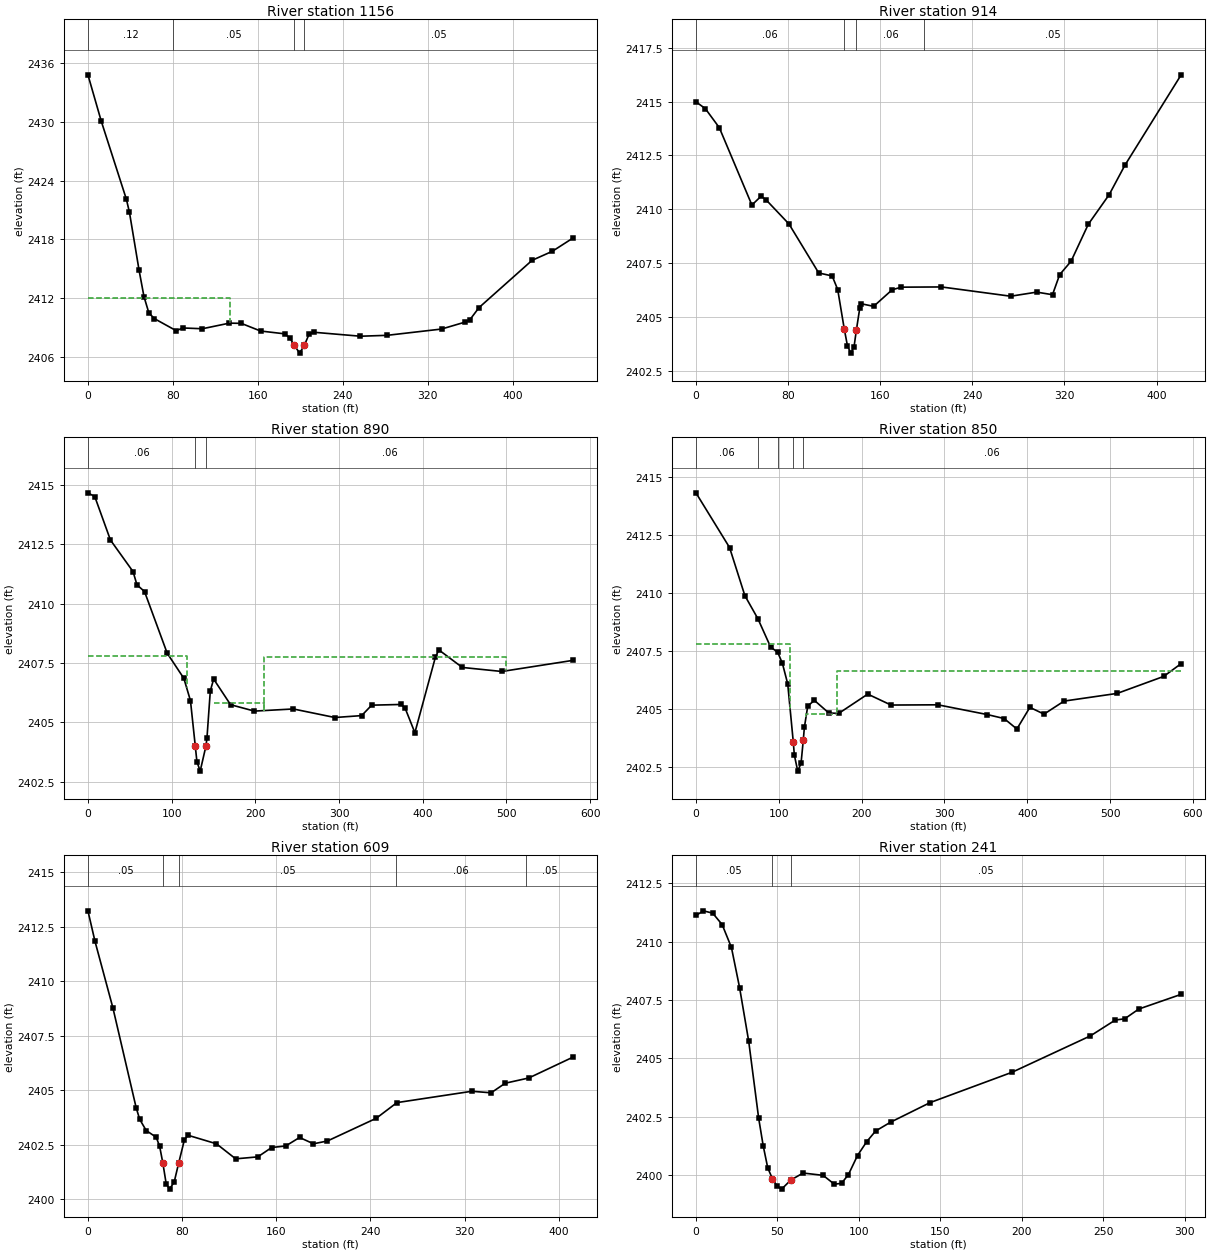
Type RM Length L Ch R = 1 ,1156    ,241.8,241.8,241.8
XS GIS Cut Line= 2
2263110.28151772450638.0826966062262711.08588934 450860.72909302
#Sta/Elev= 30
       0 2434.75    12.6 2430.02    36.2  2422.1    39.1 2420.77    48.2 2414.86
    52.8 2412.19    57.4 2410.53    62.6 2409.95    83.2 2408.72    89.4    2409
   107.8 2408.92   133.2 2409.49   144.4 2409.47   162.6 2408.69   185.6  2408.4
   190.2 2407.98   194.2 2407.27   199.4 2406.44   203.9 2407.24   208.5 2408.41
   213.1 2408.56   256.7 2408.16   281.8 2408.25   333.1 2408.89   355.1 2409.59
   359.7 2409.82   368.4 2411.07   418.4 2415.88   437.5  2416.8   457.1 2418.16
#Mann= 4 ,-1,0
       0     .12       0      80     .05       0   194.2    .045       0
   203.9     .05       0
#XS Ineff= 2 , 0
           133.8 2412.04
Permanent Ineff=
       F       F
Bank Sta=194.2,203.9
XS Rating Curve= 0 ,0
Exp/Cntr=0.3,0.1

Type RM Length L Ch R = 1 ,914     ,23.8,23.8,23.8
BEGIN DESCRIPTION:
Structure XS 4
END DESCRIPTION:
XS GIS Cut Line= 3
2262952.28729219450537.3969854052262835.00973894450553.273099333
2262608.76644231450754.760290555
#Sta/Elev= 30
       0 2414.99     8.2 2414.67    20.3 2413.79    48.6  2410.2    56.6 2410.61
    61.1 2410.43    80.8 2409.32   106.6 2407.05   118.3 2406.91   123.1 2406.28
128.77822404.458   131.6 2403.66   134.5 2403.33   137.3 2403.63139.37822404.424
   142.3 2405.43   143.6 2405.62   154.3  2405.5   170.4 2406.27   178.4 2406.39
   213.2  2406.4   273.3 2405.97   295.9 2406.16   309.6 2406.04   315.8 2406.97
   325.7 2407.59   340.7 2409.31   358.8 2410.68   372.4 2412.04   421.3 2416.24
#Mann= 4 ,-1,0
       0     .06       0128.7782    .045       0139.3782     .06       0
  198.35     .05       0
Bank Sta=128.7782,139.3782
XS Rating Curve= 0 ,0
Exp/Cntr(USF)=0,0
Exp/Cntr=0.5,0.3

Type RM Length L Ch R = 1 ,890     ,40.2,40.2,40.2
BEGIN DESCRIPTION:
Structure XS 3;  9.8 ft between structure and xs
END DESCRIPTION:
XS GIS Cut Line= 6
2262918.01554106450471.4873386862262883.45010094450501.671244142
2262814.42495757 450544.758771362262679.94734796450560.804395235
2262546.66634523450557.4775135232262364.38341176450540.174307396
#Sta/Elev= 30
       0 2414.67     8.2 2414.51    26.9 2412.68    53.9 2411.35    58.6 2410.79
    67.6 2410.51    94.7 2407.91   114.6 2406.85   122.5 2405.91  128.21 2404.01
   130.2 2403.34   134.1 2402.94     141    2404   142.2 2404.33   146.2 2406.32
   150.2 2406.82   170.4 2405.74   198.9 2405.47   245.4 2405.56     295  2405.2
     327 2405.28     339 2405.72   374.2 2405.75   379.1 2405.58   390.6 2404.56
   415.1 2407.74   419.2 2408.05   447.3 2407.31   494.5 2407.14   579.7 2407.61
#Mann= 3 ,-1,0
       0     .06       0  128.21    .045       0     141     .06       0
#XS Ineff= 3 ,-1
       0     118  2407.8     151     210  2405.8     210     500 2407.73
Permanent Ineff=
       F       F       F
Bank Sta=128.21,141
XS Rating Curve= 0 ,0
Exp/Cntr=0.5,0.3

Type RM Length L Ch R = 1 ,850     ,240.8,240.8,240.8
BEGIN DESCRIPTION:
Structure XS 2; 10.9 ft between structure and xs
END DESCRIPTION:
XS GIS Cut Line= 6
2262899.51572804450455.9085487732262838.66107994450498.750221034
2262766.12233941450512.8684993922262712.61051065450534.954357529
2262602.54504532450538.6708701862262335.04866139 450516.67080929
#Sta/Elev= 30
       0  2414.3    40.6 2411.95    59.1 2409.88    74.8 2408.89    90.2 2407.67
    98.7 2407.45   104.4 2406.97   110.8 2406.09117.46372403.613   118.8 2403.03
   122.9 2402.34   126.9 2402.68129.57372403.661   130.9 2404.22     135 2405.14
     143 2405.38   160.4 2404.84   172.3 2404.82   207.4 2405.65   235.5 2405.18
   292.1 2405.19   351.8 2404.77     372  2404.6   387.4 2404.15   403.1 2405.08
   420.2 2404.79   444.4 2405.35   508.5 2405.68   564.6 2406.41   585.7 2406.96
#Mann= 5 ,-1,0
       0     .06       0    74.8     .05       0    98.7     .06       0
117.4637    .045       0129.5737     .06       0
#XS Ineff= 3 ,-1
       0     114  2407.8   132.9     170 2404.81     170     600 2406.66
Permanent Ineff=
       F       F       F
Bank Sta=117.4637,129.5737
XS Rating Curve= 0 ,0
Exp/Cntr=0.5,0.3

Type RM Length L Ch R = 1 ,609     ,367.9,367.9,367.9
BEGIN DESCRIPTION:
Structure XS 1
END DESCRIPTION:
XS GIS Cut Line= 3
2262649.71306154450312.7220485582262472.60786258450505.823897305
2262322.47481905450505.129553195
#Sta/Elev= 30
       0 2413.24       6 2411.84    21.2 2408.79      41  2404.2      44 2403.67
    49.5 2403.16      58 2402.85    60.9 2402.44    63.7 2401.65    66.5 2400.71
    69.4 2400.47    73.3  2400.877.110342401.673      82 2402.74    85.1 2402.94
   109.2 2402.55   125.5 2401.86   144.3 2401.95   156.1 2402.38     168 2402.45
   179.8 2402.84   191.6 2402.55   203.5 2402.68   244.9 2403.72   262.5 2404.44
   326.1 2404.96   342.5 2404.89   354.5 2405.33   374.5 2405.57   412.2 2406.53
#Mann= 5 ,-1,0
       0     .05       0    63.7    .045       077.11034     .05       0
  262.02     .06       0  372.02     .05       0
Bank Sta=63.7,77.11034
XS Rating Curve= 0 ,0
Exp/Cntr(USF)=0,0
Exp/Cntr=0.3,0.1

Type RM Length L Ch R = 1 ,241     ,170.2,170.2,170.2
XS GIS Cut Line= 2
2262343.36881862450117.9458402962262136.04076628450331.841491324
#Sta/Elev= 30
       0 2411.12     4.6 2411.32    10.3 2411.22    16.1 2410.73    21.8 2409.75
    26.8 2408.03    32.4 2405.73    38.5 2402.44    41.3 2401.25    44.1  2400.3
46.973052399.834    49.8 2399.52    52.6 2399.3958.273042399.781    65.8 2400.08
    78.1 2399.98      85  2399.6    89.4 2399.64    93.6 2400.01    99.2 2400.83
   104.8 2401.42   110.3 2401.88   119.5 2402.26   143.8  2403.1   194.1  2404.4
   242.2 2405.96   257.5 2406.64   263.2 2406.69   271.9 2407.11   297.9 2407.74
#Mann= 3 ,-1,0
       0     .05       046.97305    .045       058.27304     .05       0
Bank Sta=46.97305,58.27304
XS Rating Curve= 0 ,0
Exp/Cntr(USF)=0,0
Exp/Cntr=0.3,0.1

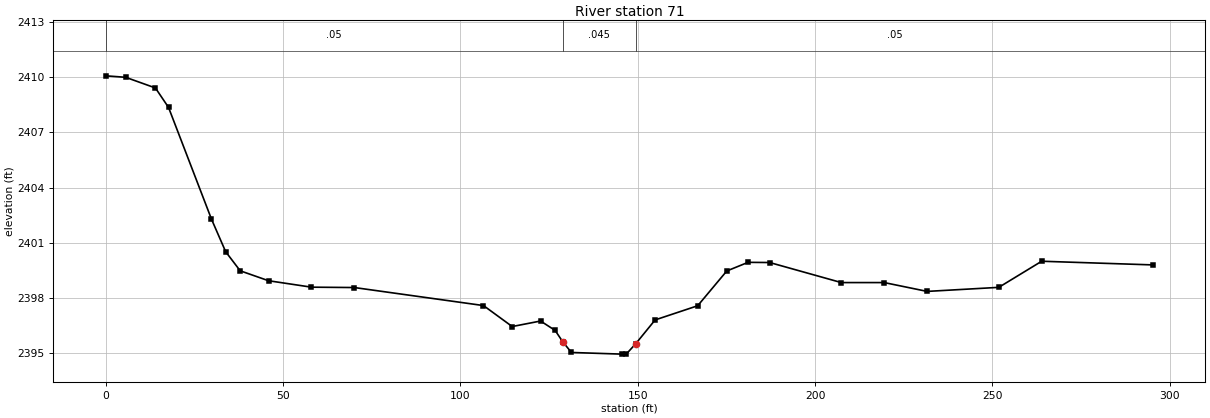
Type RM Length L Ch R = 1 ,71      ,281.7,299.2,316.2
XS GIS Cut Line= 2
2262373.68818925450039.4187865742262081.08357795 449999.76776142
#Sta/Elev= 30
       0 2410.08     5.6    2410      14 2409.42    17.7 2408.36    29.8 2402.29
    33.8 2400.52    37.9 2399.48    45.9 2398.94      58 2398.59    70.1 2398.57
   106.5 2397.59   114.6 2396.45   122.6 2396.75   126.7 2396.24128.86072395.619
   131.3 2395.04   145.5 2394.95   146.8 2394.96149.47052395.524   154.9 2396.81
   166.9 2397.58   175.1 2399.47   181.1 2399.94   187.2 2399.93   207.4 2398.84
   219.5 2398.84   231.6 2398.36   251.8 2398.58   263.9    2400   295.3  2399.8
#Mann= 3 ,-1,0
       0     .05       0128.8607    .045       0149.4705     .05       0
Bank Sta=128.8607,149.4705
XS Rating Curve= 0 ,0
Exp/Cntr=0.3,0.1
LCMann Table=0

Chan Stop Cuts=-1
Use User Specified Reach Order=0
Composite Channel Slope=5